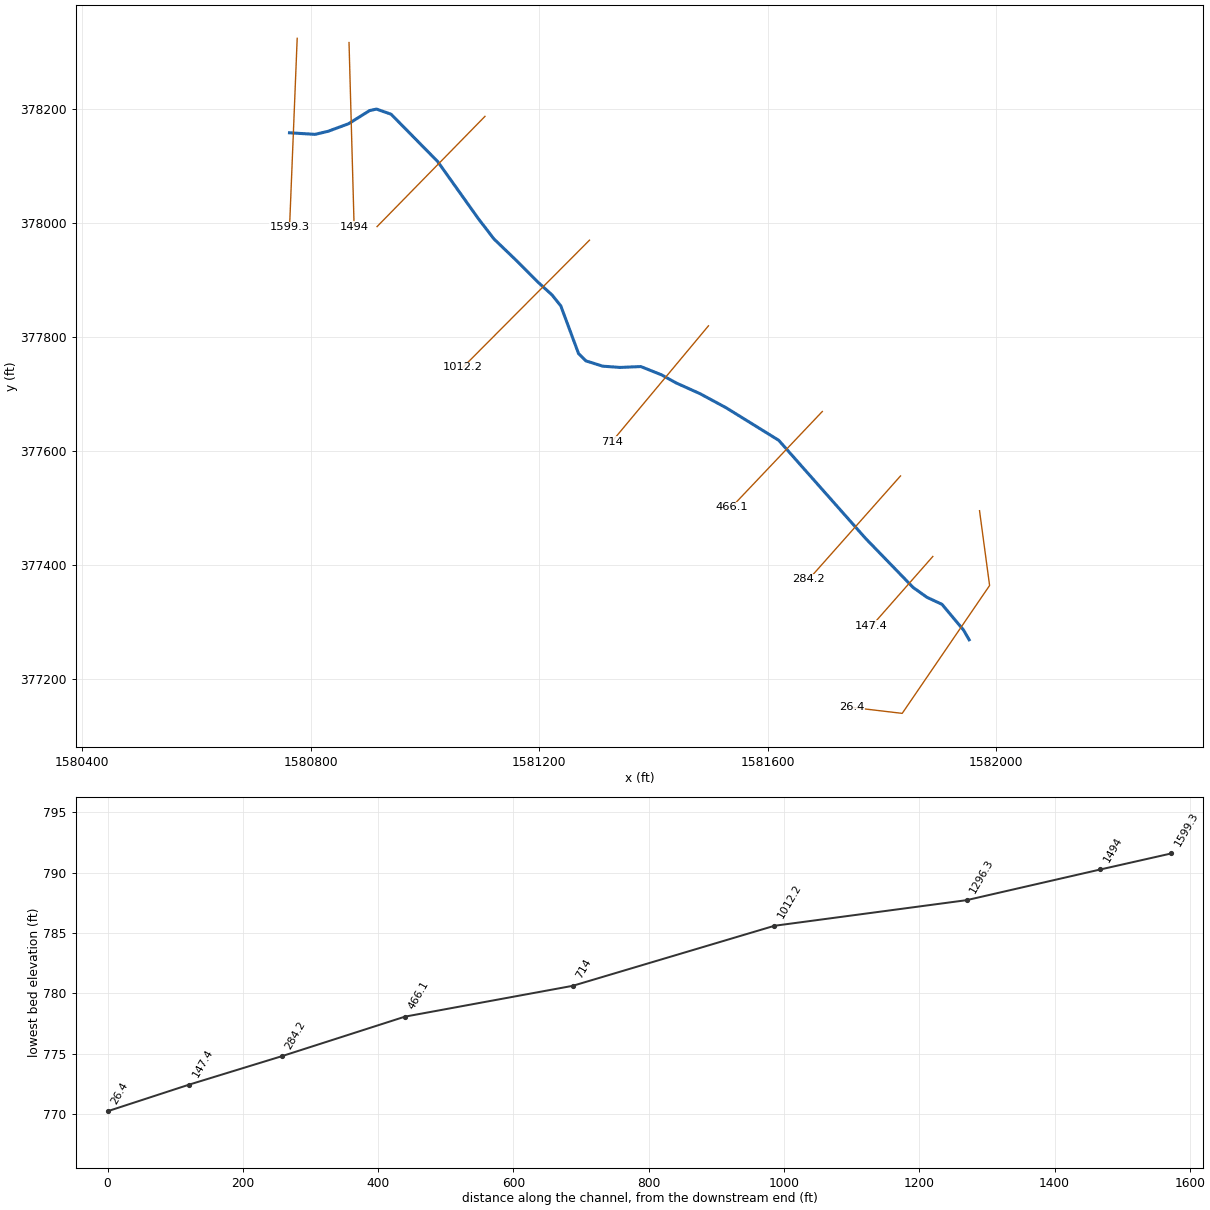
--- HNYTRACFK.prj (project) ---

Proj Title=HNYTRACFK
Current Plan=p01
Default Exp/Contr=0,0
English Units
Geom File=g01
Flow File=f01
Plan File=p01
BEGIN DESCRIPTION:
END DESCRIPTION:
DSS Export Rating Curves= 0
DSS Export Rating Curve Sorted= 0
DSS Export Volume Flow Curves= 0
DXF OffsetX= 0
DXF OffsetY= 0
DXF ScaleX= 0
DXF ScaleY= 0

--- HNYTRACFK.p01 (plan) ---

Plan Title=Floodplain
Program Version=4.00
Geom File=g01
Flow File=f01
K Sum by GR=0
Std Step Tol=0.01
Critical Tol=0.01
Num of Std Step Trials=20
Max Error Tol=0.3
Flow Tol Ratio=0.001
Split Flow NTrial=30
Split Flow Tol=0.02
Split Flow Ratio=0.02
Log Output Level=0
Friction Slope Method=1
Unsteady Friction Slope Method=2
Unsteady Bridges Friction Slope Method=1
Global Log Level=0
CheckData=False
Run HTab=0
Run UNet=0
Run PostProcess=0
UNET Theta=0
UNET Theta Warmup=0
UNET ZTol=0
UNET ZSATol=0
UNET MxIter=0
UNET MaxInSteps=0
UNET DtIC=0
UNET DtMin=0
UNET MaxCRTS=0
UNET WFStab=0
UNET SFStab=0
UNET WFX=0
UNET SFX=0
UNET DSS MLevel=0
UNET DZMax Abort=0
UNET Convert EG Bridges=0
UNET Use Existing IB Tables=0
UNET Froude Limit=0
UNET Froude Power=0
Write IC File=0
Echo Input=False
Echo Output=False
Write Detailed=0

--- HNYTRACFK.f01 (steady flow) ---

Flow Title=NFF Regression Equation
Program Version=4.00
Number of Profiles=1
Profile Names=P100yr
River Rch & RM=HNYTRACFK,Main      ,1599.3
330.7261
River Rch & RM=HNYTRACFK,Main      ,1494
370.8797
River Rch & RM=HNYTRACFK,Main      ,284.2
381.3417
Boundary for River Rch & Prof#=HNYTRACFK,Main      ,1
Up Type=0
Dn Type=3
Dn Slope=0.017805

--- HNYTRACFK.g01 (geometry) ---

Geom Title=Geometry
Program Version=4.00

River Reach=HNYTRACFK       ,Main
Reach XY= 30
     1580762.675      378158.009     1580807.398      378155.223
     1580830.365      378160.628     1580866.049      378173.846
     1580902.939      378196.937      1580915.05      378199.569
     1580940.608      378190.529     1581022.122        378107.6
     1581093.247      378007.484      1581120.64        377971.8
      1581161.93      377932.007     1581197.386      377896.267
     1581222.312      377873.561      1581237.68      377854.412
     1581268.818      377770.628     1581281.815      377757.802
     1581311.041      377748.526     1581341.527      377746.313
     1581377.719      377747.864     1581413.824      377733.482
     1581439.404      377719.253     1581481.383      377700.329
     1581527.141      377675.612     1581619.319      377618.476
     1581771.305      377446.434     1581854.612      377360.307
     1581878.893      377342.984     1581905.082       377330.76
     1581942.915      377285.585     1581952.751      377268.434

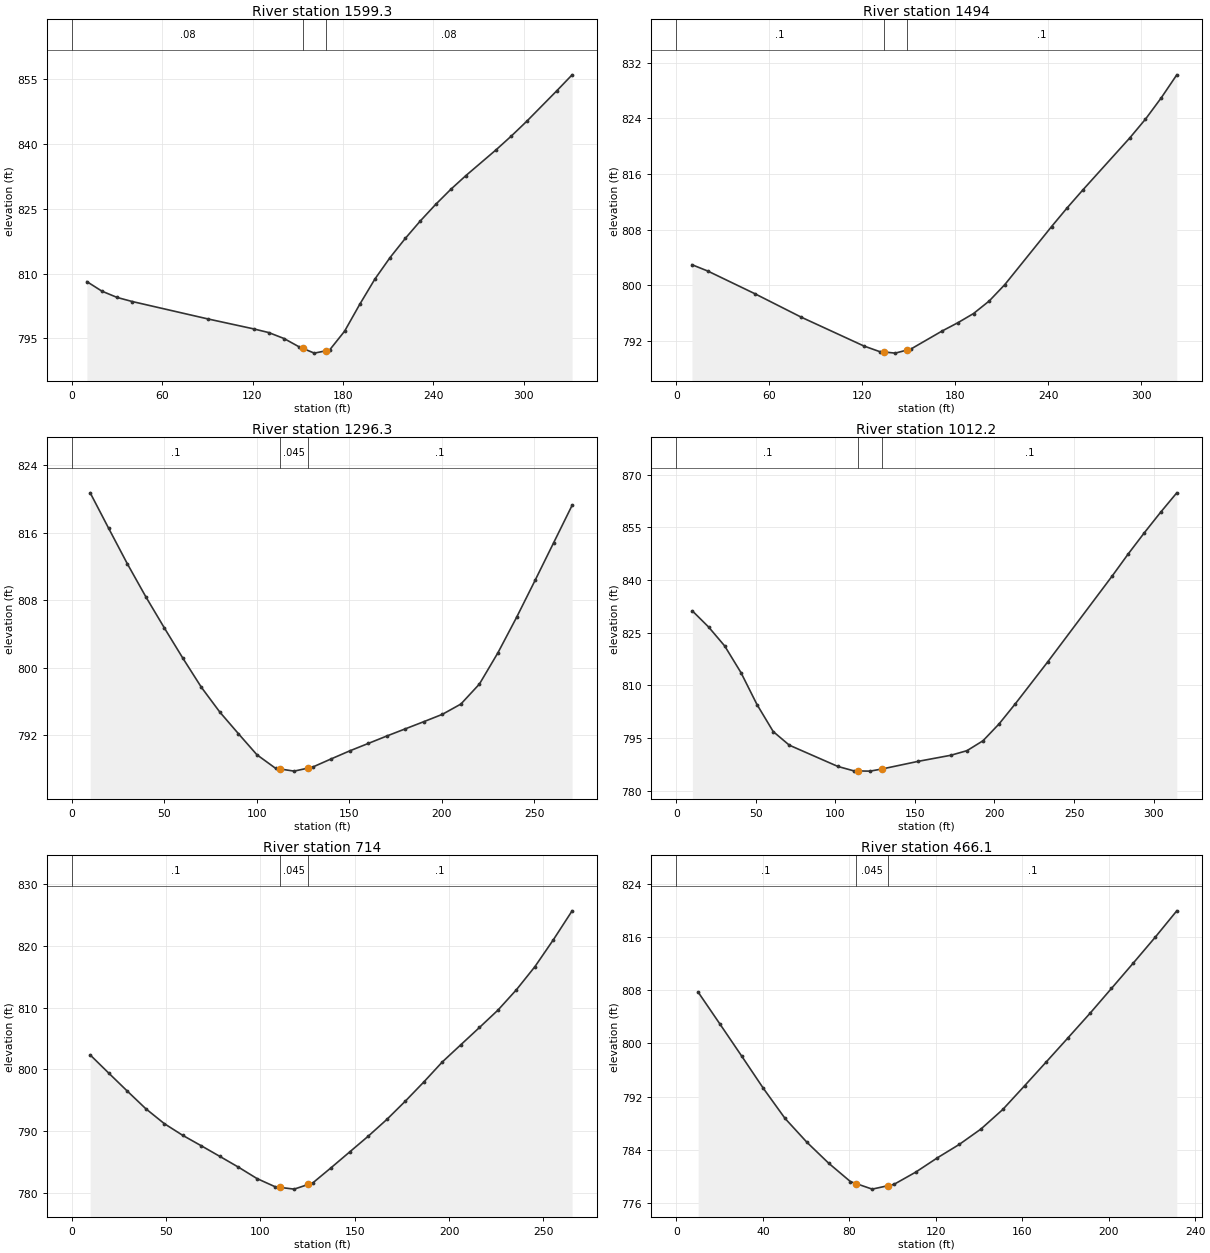
Type RM Length L Ch R = 1 ,1599.3  ,104.9,105.2,106
XS GIS Cut Line= 2
     1580776.179      378323.697     1580762.789      377991.913
#Sta/Elev= 27
    10.1  808.12    20.1  805.91    30.2  804.46    40.2  803.52    90.6  799.48
   120.7   797.2   130.8  796.34   140.9  794.97   150.9  793.05   153.5  792.67
     161  791.59   168.5  792.11   171.1  792.29   181.1  796.66   191.2   802.9
   201.2  808.71   211.3   813.7   221.4  818.12   231.4  822.17   241.5  825.96
   251.6  829.47   261.6  832.64   281.7  838.62   291.8   841.8   301.9  845.17
     322  852.28   332.1  855.94
#Mann= 3 , 0 , 0
       0     .08       0   153.5    .045       0   168.5     .08       0
Bank Sta=153.5,168.5
XS Rating Curve= 0 ,0
Exp/Cntr=0.3,0.1

Type RM Length L Ch R = 1 ,1494    ,215,197.7,179.9
XS GIS Cut Line= 2
     1580866.936      378316.258     1580875.863      377993.401
#Sta/Elev= 22
    10.1  802.97    20.2  802.07    50.5  798.82    80.7  795.42   121.1  791.28
   131.2  790.48   133.8  790.43   141.3  790.26   148.8   790.7   151.4  790.85
   171.6  793.45   181.7  794.63   191.8  795.95   201.9  797.75     212  800.11
   242.2  808.46   252.3  811.16   262.4  813.73   292.7  821.21   302.8   823.9
   312.9  826.94     323  830.27
#Mann= 3 , 0 , 0
       0      .1       0   133.8    .045       0   148.8      .1       0
Bank Sta=133.8,148.8
XS Rating Curve= 0 ,0
Exp/Cntr=0.3,0.1

Type RM Length L Ch R = 1 ,1296.3  ,284.3,284.1,283.9
XS GIS Cut Line= 2
     1581104.988      378186.817     1580916.035      377993.401
#Sta/Elev= 29
      10  820.74      20  816.52      30  812.35    40.1  808.39    50.1   804.7
    60.1  801.11    70.1  797.66    80.1  794.71    90.1  792.16   100.1  789.66
   110.2  788.05   112.7  787.97   120.2  787.72   127.7  788.08   130.2   788.2
   140.2  789.17   150.2  790.12   160.2     791   170.2  791.88   180.3  792.74
   190.3  793.59   200.3  794.46   210.3  795.68   220.3  798.05   230.3  801.76
   240.4  805.97   250.4  810.36   260.4  814.81   270.4  819.26
#Mann= 3 , 0 , 0
       0      .1       0   112.7    .045       0   127.7      .1       0
Bank Sta=112.7,127.7
XS Rating Curve= 0 ,0
Exp/Cntr=0.3,0.1

Type RM Length L Ch R = 1 ,1012.2  ,296.1,298.2,300.3
XS GIS Cut Line= 2
      1581287.99      377969.596     1581066.305      377746.423
#Sta/Elev= 24
    10.1  831.19    20.3  826.61    30.4  821.22    40.6  813.66    50.7  804.55
    60.9  796.86      71  792.99   101.5  786.94   111.6  785.67   114.3  785.65
   121.8   785.6   129.3  786.21   152.2   788.4   172.5  790.11   182.7  791.42
   192.8  794.25   202.9  799.05   213.1  804.77   233.4  816.66     274  841.14
   284.1  847.44   294.3   853.5   304.4  859.26   314.6  864.81
#Mann= 3 , 0 , 0
       0      .1       0   114.3    .045       0   129.3      .1       0
Bank Sta=114.3,129.3
XS Rating Curve= 0 ,0
Exp/Cntr=0.3,0.1

Type RM Length L Ch R = 1 ,714     ,249.3,247.9,246.4
XS GIS Cut Line= 2
     1581496.285      377819.326     1581326.673      377615.494
#Sta/Elev= 29
     9.8  802.34    19.6  799.41    29.5  796.48    39.3  793.63    49.1  791.22
    58.9  789.32    68.7  787.64    78.6  785.91    88.4  784.18    98.2  782.34
     108  780.99   110.4  780.91   117.9  780.63   125.4  781.39   127.7  781.62
   137.5   784.1   147.3  786.64   157.1  789.18     167   791.9   176.8  794.86
   186.6  797.96   196.4   801.2   206.2  803.98   216.1  806.78   225.9  809.59
   235.7  812.89   245.5  816.63   255.3  820.99   265.2  825.65
#Mann= 3 , 0 , 0
       0      .1       0   110.4    .045       0   125.4      .1       0
Bank Sta=110.4,125.4
XS Rating Curve= 0 ,0
Exp/Cntr=0.3,0.1

Type RM Length L Ch R = 1 ,466.1   ,181.1,181.9,182.6
XS GIS Cut Line= 2
     1581695.653      377669.056     1581536.456      377500.932
#Sta/Elev= 25
    10.1  807.71    20.1  802.95    30.2  798.11    40.3  793.22    50.3  788.71
    60.4  785.13    70.5  781.97    80.5  779.22    83.1  778.92    90.6  778.08
    98.1  778.61   100.7   778.8   110.7  780.63   120.8   782.8   130.9  784.81
   140.9  787.12     151  790.06   161.1  793.63   171.1  797.21   181.2  800.85
   191.3  804.51   201.3  808.28   211.4   812.1   221.5  815.97   231.5  819.95
#Mann= 3 , 0 , 0
       0      .1       0    83.1    .045       0    98.1      .1       0
Bank Sta=83.1,98.1
XS Rating Curve= 0 ,0
Exp/Cntr=0.3,0.1

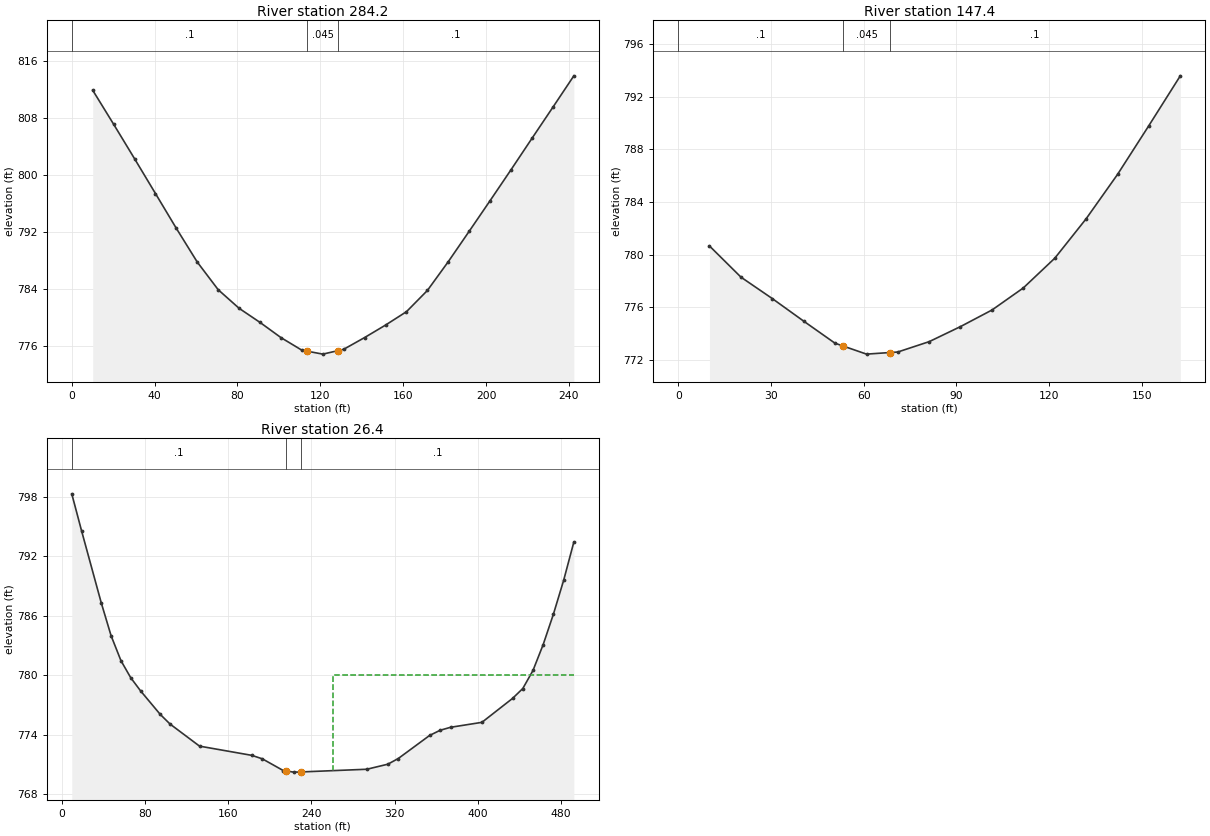
Type RM Length L Ch R = 1 ,284.2   ,136.7,136.8,136.9
XS GIS Cut Line= 2
     1581832.532      377555.981     1581671.848      377374.467
#Sta/Elev= 26
    10.1  811.86    20.2  807.09    30.3  802.25    40.4  797.36    50.5  792.46
    60.6  787.73    70.7  783.85    80.8  781.24    90.9  779.26     101  777.13
   111.1  775.36   113.7  775.22   121.2  774.81   128.7  775.31   131.3  775.49
   141.4  777.14   151.5  778.89   161.6  780.77   171.7  783.75   181.8   787.8
   191.9  792.07     202  796.37   212.1  800.71   222.2  805.11   232.3  809.48
   242.4  813.88
#Mann= 3 , 0 , 0
       0      .1       0   113.7    .045       0   128.7      .1       0
Bank Sta=113.7,128.7
XS Rating Curve= 0 ,0
Exp/Cntr=0.3,0.1

Type RM Length L Ch R = 1 ,147.4   ,118.3,121,123.9
XS GIS Cut Line= 2
      1581889.07      377414.638     1581781.946      377292.637
#Sta/Elev= 18
    10.1  780.67    20.3   778.3    30.4  776.68    40.6  774.96    50.7  773.29
    53.4  773.07    60.9  772.46    68.4  772.58      71  772.62    81.2  773.41
    91.3  774.55   101.5  775.81   111.6  777.48   121.8  779.74   131.9  782.72
   142.1   786.1   152.2  789.79   162.4  793.58
#Mann= 3 , 0 , 0
       0      .1       0    53.4    .045       0    68.4      .1       0
Bank Sta=53.4,68.4
XS Rating Curve= 0 ,0
Exp/Cntr=0.3,0.1

Type RM Length L Ch R = 1 ,26.4    ,36.7,26.4,15.9
XS GIS Cut Line= 4
       1581970.9      377494.981     1581988.523      377363.737
     1581835.508      377139.392     1581747.726      377149.806
#Sta/Elev= 30
     9.5  798.31    18.9  794.59    37.8  787.34    47.3  784.01    56.8  781.49
    66.2  779.77    75.7  778.44    94.6  776.07     104   775.1   132.4  772.87
   182.7  771.94   192.8  771.59   212.9  770.41   215.4  770.37   222.9  770.25
   230.4  770.27   293.3  770.54   313.5  771.05   323.5  771.62   353.7  773.95
   363.8  774.47   373.8  774.77     404  775.27   433.4  777.68   443.3  778.68
   453.1   780.5   462.9  783.11   472.7  786.16   482.6  789.59   492.4  793.45
#Mann= 3 , 0 , 0
     9.5      .1       0   215.4    .045       0   230.4      .1       0
#XS Ineff= 2 , 0
                          260.91          780.07
Permanent Ineff=
       F       F
Bank Sta=215.4,230.4
XS Rating Curve= 0 ,0
Exp/Cntr=0.3,0.1

Chan Stop Cuts=-1
Use User Specified Reach Order=0